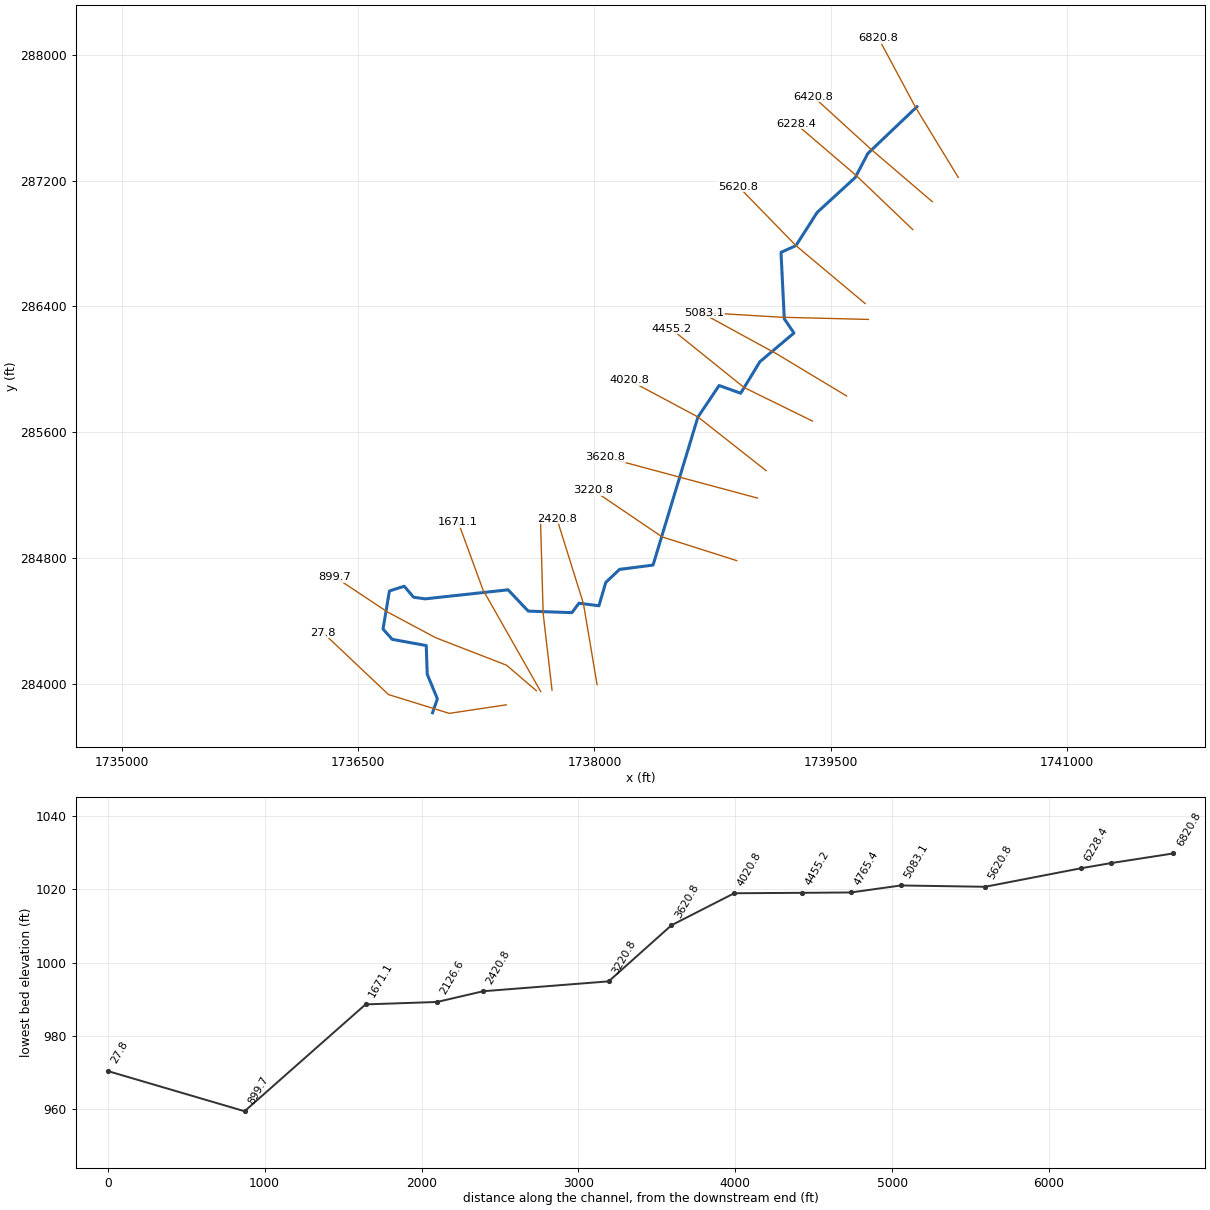
--- MurphyRn.prj (project) ---

Proj Title=MurphyRn
Current Plan=p01
Default Exp/Contr=0,0
English Units
Geom File=g01
Flow File=f01
Plan File=p01
BEGIN DESCRIPTION:
END DESCRIPTION:
DSS Export Rating Curves= 0
DSS Export Rating Curve Sorted= 0
DSS Export Volume Flow Curves= 0
DXF OffsetX= 0
DXF OffsetY= 0
DXF ScaleX= 0
DXF ScaleY= 0

--- MurphyRn.p01 (plan) ---

Plan Title=Floodplain
Program Version=4.00
Geom File=g01
Flow File=f01
K Sum by GR=0
Std Step Tol=0.01
Critical Tol=0.01
Num of Std Step Trials=20
Max Error Tol=0.3
Flow Tol Ratio=0.001
Split Flow NTrial=30
Split Flow Tol=0.02
Split Flow Ratio=0.02
Log Output Level=0
Friction Slope Method=1
Unsteady Friction Slope Method=2
Unsteady Bridges Friction Slope Method=1
Global Log Level=0
CheckData=False
Run HTab=0
Run UNet=0
Run PostProcess=0
UNET Theta=0
UNET Theta Warmup=0
UNET ZTol=0
UNET ZSATol=0
UNET MxIter=0
UNET MaxInSteps=0
UNET DtIC=0
UNET DtMin=0
UNET MaxCRTS=0
UNET WFStab=0
UNET SFStab=0
UNET WFX=0
UNET SFX=0
UNET DSS MLevel=0
UNET DZMax Abort=0
UNET Convert EG Bridges=0
UNET Use Existing IB Tables=0
UNET Froude Limit=0
UNET Froude Power=0
Write IC File=0
Echo Input=False
Echo Output=False
Write Detailed=0

--- MurphyRn.f01 (steady flow) ---

Flow Title=NFF Regression Equation
Program Version=4.00
Number of Profiles= 1
Profile Names=P100yr
River Rch & RM=MurphyRn,Main            ,6820.8
759.9212
River Rch & RM=MurphyRn,Main            ,6228.4
 804.583
River Rch & RM=MurphyRn,Main            ,4020.8
  862.89
River Rch & RM=MurphyRn,Main            ,3220.8
922.2518
River Rch & RM=MurphyRn,Main            ,2420.8
1030.433
River Rch & RM=MurphyRn,Main            ,899.7
1063.697
River Rch & RM=MurphyRn,Main            ,27.8
1063.697
Boundary for River Rch & Prof#=MurphyRn,Main            , 1
Up Type= 0
Dn Type= 3
Dn Slope=0.003343
DSS Import GetInterval= 0
DSS Import GetPeak= 0
DSS Import FillOption= 0

--- MurphyRn.g01 (geometry) ---

Geom Title=USGS 3m DEM
Program Version=4.00

River Reach=MurphyRn     ,Main
Reach XY= 30
     1740046.982      287670.503     1739735.672      287373.515
     1739655.159      287220.164     1739414.184      286998.772
     1739279.089      286787.188     1739184.237      286744.229
     1739205.208      286321.864     1739266.310      286231.186
     1739050.295      286048.808     1738928.390      285848.368
     1738791.528      285897.533     1738656.611      285695.901
     1738372.286      284755.576     1738159.721      284728.201
     1738072.397      284645.243     1738028.736      284496.793
     1737902.117      284513.166     1737857.363      284453.131
     1737580.111      284462.955     1737452.400      284598.307
     1736925.945      284540.815     1736852.011      284551.547
     1736793.728      284621.195     1736699.373      284590.899
     1736658.829      284348.825     1736717.261      284283.239
     1736933.100      284243.887     1736939.374      284061.267
     1737003.775      283905.176     1736973.212      283816.760

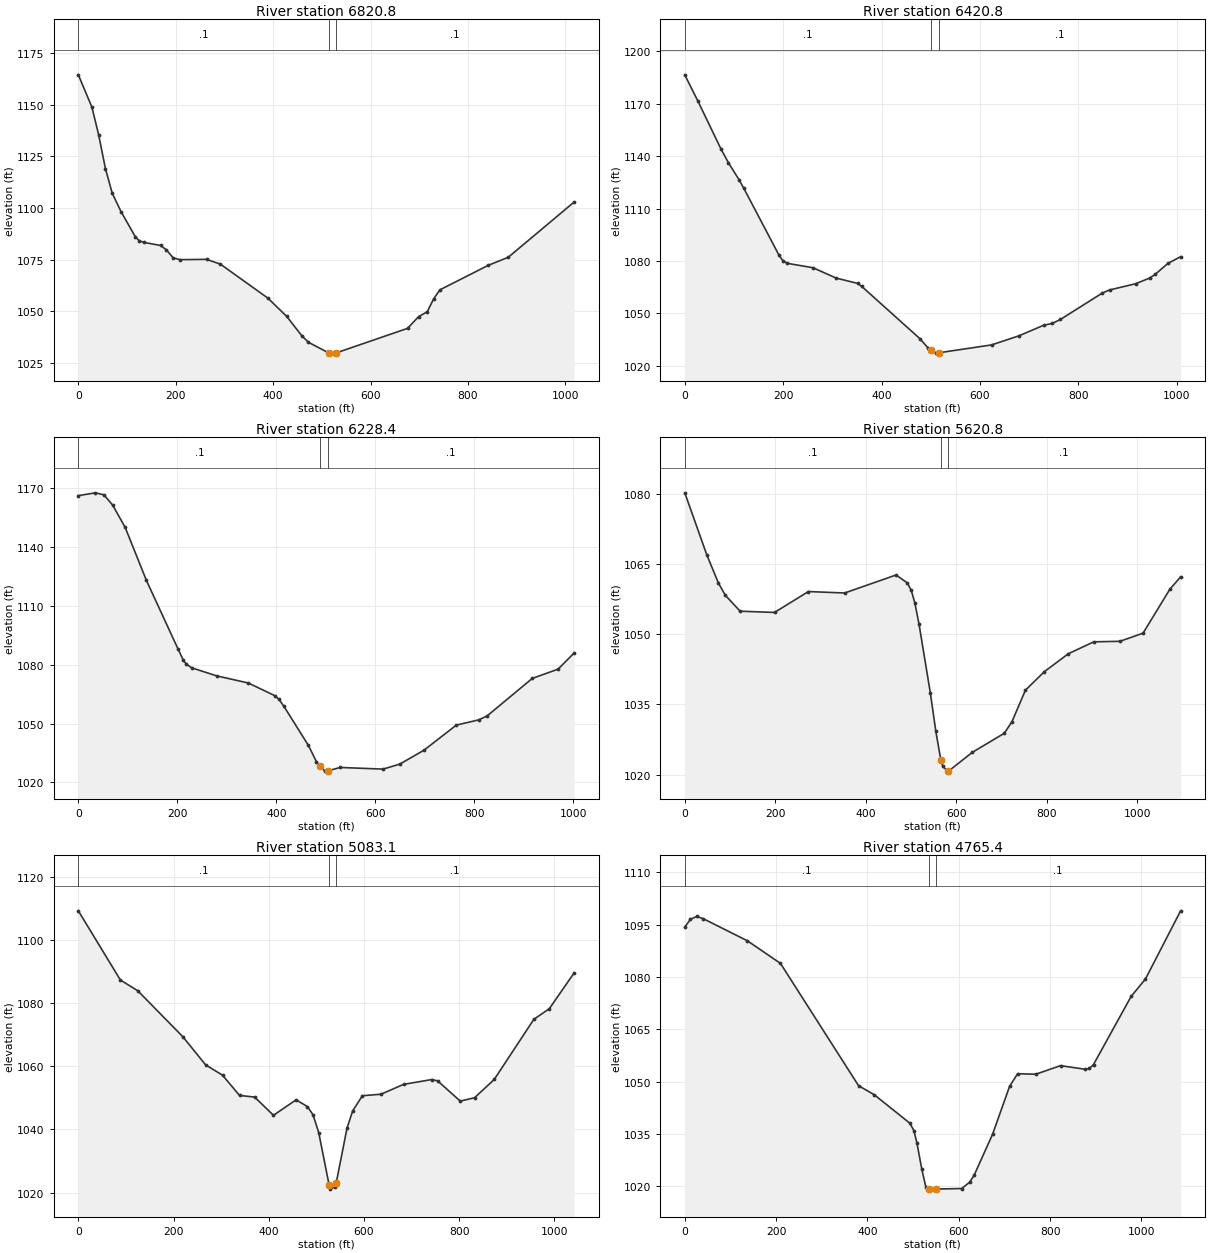
Type RM Length L Ch R = 1 ,6820.8,392.731,400,407.852
XS GIS Cut Line= 3
     1740308.672      287221.448     1740037.543      287667.327
     1739803.606      288105.225
#Sta/Elev= 30
       0 1164.38    27.8 1148.81    41.7 1135.38    55.6 1119.09    69.5 1107.20
    87.6 1098.28   116.9 1086.14   125.0 1084.18   134.2 1083.39   168.7 1081.89
   180.6 1079.83   194.5 1075.94   208.4 1075.02   263.4 1075.17   291.8 1072.84
   389.1 1056.44   428.0 1047.56   458.5 1038.33   472.4 1035.08   514.3 1029.92
   527.8 1029.84   529.3 1029.94   675.9 1041.81   698.5 1047.45   716.3 1049.83
   729.7 1056.15   742.4 1060.44   841.6 1072.29   882.7 1076.18  1018.0 1102.89
#Mann= 3 , 0 , 0
       0     0.1       0   514.3   0.045       0   529.3     0.1       0
Bank Sta=   514.3,   529.3
Exp/Cntr=0.3,0.1

Type RM Length L Ch R = 1 ,6420.8,193.771,192.407,192.668
XS GIS Cut Line= 3
     1740144.254      287066.618     1739757.870      287397.814
     1739389.448      287734.389
#Sta/Elev= 30
       0 1186.62    26.3 1171.76    73.7 1144.04    88.8 1136.21   110.2 1126.54
   120.1 1121.53   191.3 1083.40   199.7 1080.03   208.1 1078.65   260.8 1076.09
   307.7 1070.17   351.3 1067.13   359.7 1065.40   477.6 1035.54   494.4 1030.18
   501.4 1028.89   511.1 1027.18   516.4 1027.38   623.7 1031.89   679.3 1037.10
   729.8 1043.18   746.6 1044.16   763.4 1046.45   848.8 1061.62   863.5 1063.38
   916.3 1066.93   945.3 1070.22   956.7 1072.42   981.9 1078.56  1007.9 1082.43
#Mann= 3 , 0 , 0
       0     0.1       0   501.4   0.045       0   516.4     0.1       0
Bank Sta=   501.4,   516.4
Exp/Cntr=0.3,0.1

Type RM Length L Ch R = 1 ,6228.4,606.053,607.593,606.065
XS GIS Cut Line= 3
     1740020.590      286888.775     1739658.554      287235.701
     1739278.768      287561.430
#Sta/Elev= 30
       0 1166.30    34.6 1167.73    51.8 1166.70    69.6 1161.38    94.7 1150.05
   137.6 1123.01   201.7 1087.91   212.3 1082.32   218.1 1080.36   229.1 1078.45
   279.5 1074.36   343.5 1070.71   397.0 1064.25   405.4 1062.38   415.4 1058.81
   464.8 1038.90   481.0 1030.62   489.1 1028.27   498.0 1025.76   504.1 1025.90
   529.1 1027.63   615.7 1026.79   649.4 1029.33   698.4 1036.44   763.7 1049.23
   809.3 1051.93   826.0 1053.94   917.2 1073.06   969.3 1077.78  1001.8 1086.05
#Mann= 3 , 0 , 0
       0     0.1       0   489.1   0.045       0   504.1     0.1       0
Bank Sta=   489.1,   504.1
Exp/Cntr=0.3,0.1

Type RM Length L Ch R = 1 ,5620.8,498.938,537.639,542.28
XS GIS Cut Line= 3
     1739718.196      286418.592     1739278.961      286787.174
     1738914.549      287162.341
#Sta/Elev= 30
       0 1080.24    48.4 1067.04    74.3 1060.95    89.8 1058.31   122.3 1054.93
   198.3 1054.66   273.2 1059.13   353.3 1058.82   467.0 1062.67   491.7 1060.99
   500.7 1059.36   508.3 1056.78   517.6 1052.25   542.8 1037.43   554.8 1029.30
   565.9 1023.13   570.3 1021.75   580.9 1020.74   582.9 1020.73   635.3 1024.73
   706.3 1028.83   723.3 1031.33   752.9 1038.03   794.8 1042.00   847.8 1045.83
   904.0 1048.38   961.9 1048.49  1013.0 1050.23  1071.9 1059.58  1096.0 1062.28
#Mann= 3 , 0 , 0
       0     0.1       0   565.9   0.045       0   580.9     0.1       0
Bank Sta=   565.9,   580.9
Exp/Cntr=0.3,0.1

Type RM Length L Ch R = 1 ,5083.1,327.047,317.733,278.563
XS GIS Cut Line= 3
     1739738.514      286317.738     1739183.466      286331.798
     1738698.279      286361.032
#Sta/Elev= 30
       0 1109.27    88.3 1087.35   124.8 1083.95   219.8 1069.33   267.3 1060.46
   302.9 1057.19   338.5 1050.78   370.3 1050.25   409.8 1044.48   457.3 1049.38
   481.1 1047.26   492.9 1044.64   504.8 1039.03   526.7 1022.39   528.6 1021.09
   540.0 1021.85   541.7 1023.15   564.2 1040.35   576.1 1045.88   596.6 1050.68
   635.6 1051.16   683.2 1054.29   742.4 1055.81   754.5 1055.40   802.1 1048.98
   832.2 1050.05   873.5 1055.85   956.7 1074.90   989.2 1078.27  1041.3 1089.61
#Mann= 3 , 0 , 0
       0     0.1       0   526.7   0.045       0   541.7     0.1       0
Bank Sta=   526.7,   541.7
Exp/Cntr=0.3,0.1

Type RM Length L Ch R = 1 ,4765.4,308.815,310.22,306.439
XS GIS Cut Line= 3
     1739600.600      285830.967     1739157.609      286098.225
     1738658.869      286371.191
#Sta/Elev= 30
       0 1094.26    12.3 1096.51    26.2 1097.31    40.1 1096.70   137.1 1090.34
   209.5 1083.87   380.6 1048.81   414.4 1046.28   493.0 1038.06   501.6 1035.98
   508.3 1032.47   519.0 1024.94   527.7 1019.88   534.8 1019.35   536.5 1019.18
   549.8 1019.20   606.4 1019.35   623.9 1021.17   633.5 1023.11   674.1 1034.92
   711.4 1048.65   728.9 1052.25   768.8 1052.11   822.9 1054.57   877.1 1053.52
   886.3 1053.77   895.1 1054.88   977.4 1074.38  1008.8 1079.38  1085.9 1098.93
#Mann= 3 , 0 , 0
       0     0.1       0   534.8   0.045       0   549.8     0.1       0
Bank Sta=   534.8,   549.8
Exp/Cntr=0.3,0.1

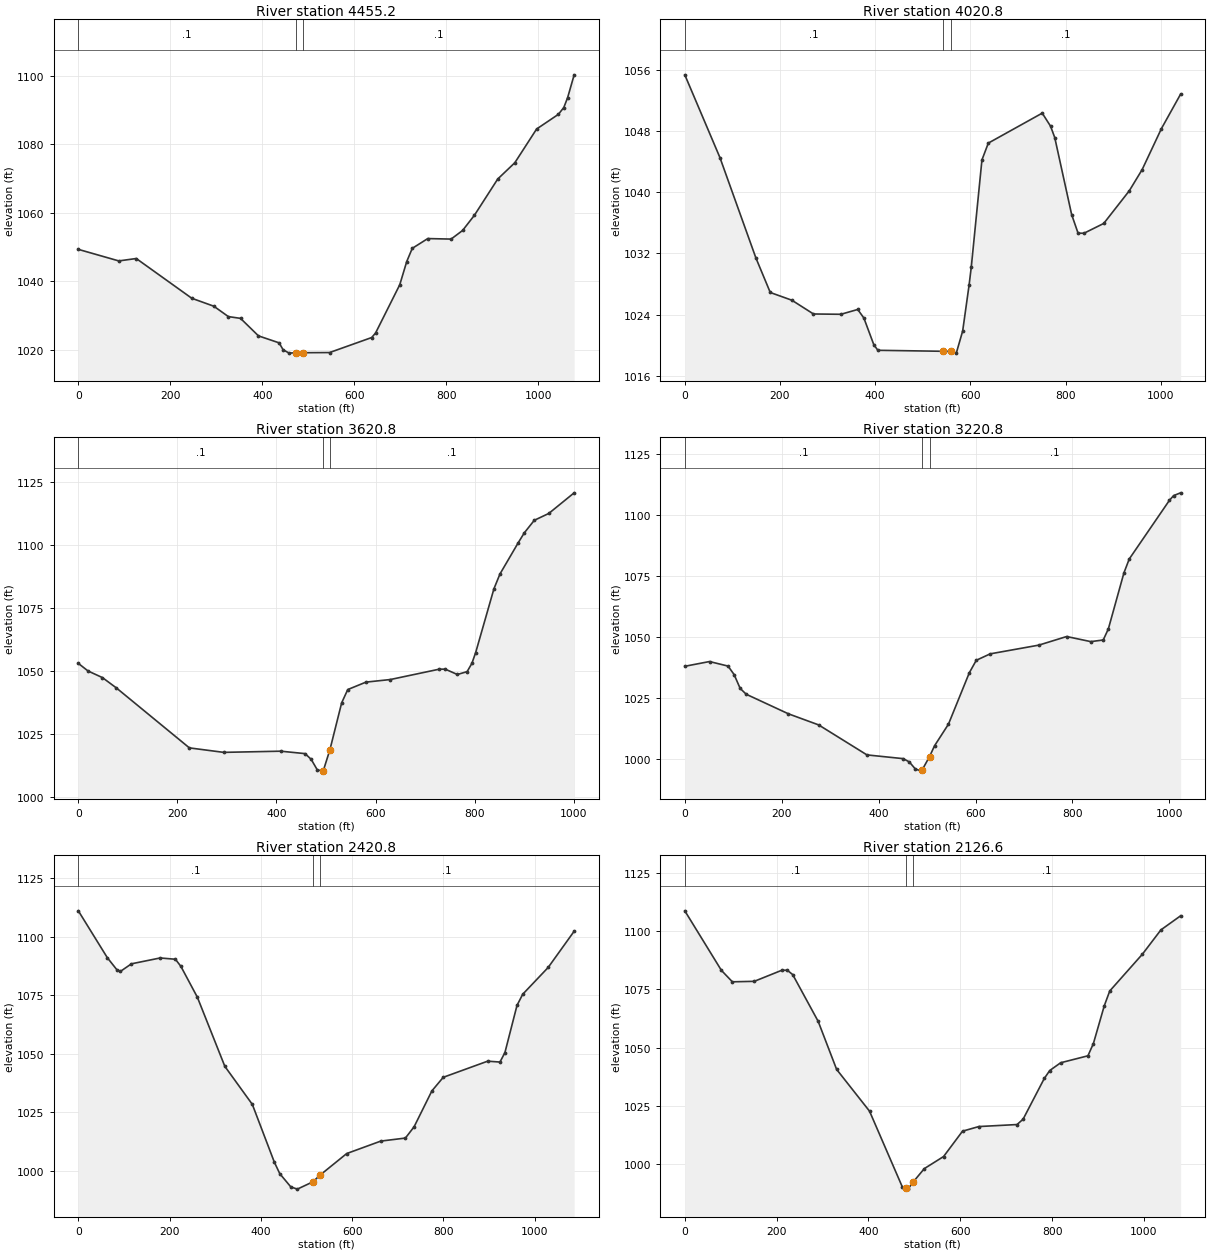
Type RM Length L Ch R = 1 ,4455.2,436.777,434.407,435.583
XS GIS Cut Line= 3
     1739383.957      285671.424     1738949.862      285884.887
     1738487.628      286257.554
#Sta/Elev= 30
       0 1049.35    87.9 1045.98   125.9 1046.68   246.6 1035.08   294.4 1032.77
   326.0 1029.74   352.5 1029.22   391.5 1024.11   436.3 1022.08   445.1 1020.04
   458.3 1019.08   472.4 1019.21   487.4 1019.20   546.0 1019.25   637.5 1023.63
   645.9 1024.94   698.5 1039.03   713.7 1045.81   725.7 1049.65   759.4 1052.50
   810.1 1052.35   835.1 1054.87   860.8 1059.31   911.4 1069.87   948.6 1074.63
   995.9 1084.46  1043.2 1088.74  1055.0 1090.73  1063.4 1093.65  1077.5 1100.27
#Mann= 3 , 0 , 0
       0     0.1       0   472.4   0.045       0   487.4     0.1       0
Bank Sta=   472.4,   487.4
Exp/Cntr=0.3,0.1

Type RM Length L Ch R = 1 ,4020.8,390.833,400,405.156
XS GIS Cut Line= 3
     1739089.928      285356.062     1738657.513      285697.349
     1738224.347      285929.396
#Sta/Elev= 30
       0 1055.36    73.8 1044.54   149.4 1031.41   179.6 1026.89   225.0 1025.88
   270.4 1024.08   328.0 1024.04   363.4 1024.67   376.3 1023.55   397.2 1020.06
   405.7 1019.33   543.4 1019.20   558.4 1019.18   570.5 1018.96   583.9 1021.85
   597.4 1027.86   602.0 1030.22   624.4 1044.23   637.8 1046.43   751.1 1050.35
   768.6 1048.64   777.4 1047.15   812.9 1037.08   826.4 1034.65   838.8 1034.64
   880.3 1035.92   934.1 1040.20   961.1 1042.97  1001.5 1048.32  1041.9 1052.84
#Mann= 3 , 0 , 0
       0     0.1       0   543.4   0.045       0   558.4     0.1       0
Bank Sta=   543.4,   558.4
Exp/Cntr=0.3,0.1

Type RM Length L Ch R = 1 ,3620.8,401.13,400,391.991
XS GIS Cut Line= 3
     1739034.792      285181.823     1738551.501      285311.939
     1738068.210      285442.056
#Sta/Elev= 30
       0 1053.01    19.6 1049.99    48.7 1047.36    76.6 1043.29   224.2 1019.45
   293.5 1017.67   408.6 1018.14   457.8 1017.17   470.1 1014.90   482.4 1010.72
     493 1010.27   494.3 1010.22     508 1018.79   531.6 1037.32   543.9 1042.61
   580.7 1045.57   629.8 1046.59   728.3 1050.69   740.6 1050.72   765.2 1048.60
   784.9 1049.73   794.6 1053.04   802.1 1057.26   839.0 1082.61   851.2 1088.51
   888.1 1100.92   900.4 1104.86   920.5 1109.83   949.7 1112.54  1001.0 1120.74
#Mann= 3 , 0 , 0
       0     0.1       0     493   0.045       0     508     0.1       0
Bank Sta=     493,     508
Exp/Cntr=0.3,0.1

Type RM Length L Ch R = 1 ,3220.8,819.194,800,786.954
XS GIS Cut Line= 3
     1738903.397      284783.903     1738429.447      284935.095
     1737994.485      285230.396
#Sta/Elev= 30
       0 1037.91    51.0 1039.86    89.3 1037.99   101.8 1034.50   114.2 1028.86
   126.7 1026.45   213.9 1018.41   276.2 1013.87   375.9 1001.56   450.7 1000.03
   463.2  998.70   475.6  995.83   488.1  994.91     490  995.45     505 1000.87
   515.4 1005.31   544.1 1014.17   587.1 1035.24   601.5 1040.37   630.2 1043.01
   730.6 1046.59   788.0 1050.12   837.8 1048.03   863.5 1048.70   874.1 1053.27
   906.2 1076.23   917.2 1081.93  1000.2 1106.02  1008.8 1107.93  1023.2 1109.06
#Mann= 3 , 0 , 0
       0     0.1       0     490   0.045       0     505     0.1       0
Bank Sta=     490,     505
Exp/Cntr=0.3,0.1

Type RM Length L Ch R = 1 ,2420.8,301.078,294.122,285.638
XS GIS Cut Line= 3
     1738016.879      283996.011     1737930.635      284510.368
     1737762.379      285049.549
#Sta/Elev= 30
       0 1111.18    63.6 1091.12    84.2 1086.05    92.3 1085.30   116.4 1088.53
   179.3 1091.03   212.7 1090.48   224.7 1087.43   260.8 1074.24   321.0 1044.69
   381.2 1028.43   429.4 1003.75   441.4  998.80   465.5  993.17   479.8  992.21
     514  995.34     529  998.11   588.0 1007.42   662.6 1012.74   716.6 1014.04
   735.6 1018.85   774.6 1034.20   799.5 1040.01   896.7 1046.90   923.8 1046.54
   934.6 1050.58   961.1 1070.76   973.6 1075.52  1029.4 1086.98  1086.3 1102.46
#Mann= 3 , 0 , 0
       0     0.1       0     514   0.045       0     529     0.1       0
Bank Sta=     514,     529
Exp/Cntr=0.3,0.1

Type RM Length L Ch R = 1 ,2126.6,447.028,455.556,461.755
XS GIS Cut Line= 3
     1737731.320      283960.354     1737675.075      284446.582
     1737658.191      285037.143
#Sta/Elev= 30
       0 1108.78    79.7 1083.22   103.6 1078.30   151.4 1078.51   211.2 1083.25
   223.2 1083.29   235.1 1081.38   290.5 1061.33   330.7 1040.69   402.4 1022.75
   474.1  990.09     482  989.55   486.1  989.28     497  992.26   521.8  998.10
   563.7 1003.28   604.9 1014.16   640.5 1016.15   723.7 1017.01   736.9 1019.32
   783.0 1036.79   794.9 1040.21   818.7 1043.54   878.1 1046.53   890.0 1051.79
   913.7 1068.00   925.6 1074.36   996.9 1090.20  1037.1 1100.60  1080.0 1106.65
#Mann= 3 , 0 , 0
       0     0.1       0     482   0.045       0     497     0.1       0
Bank Sta=     482,     497
Exp/Cntr=0.3,0.1

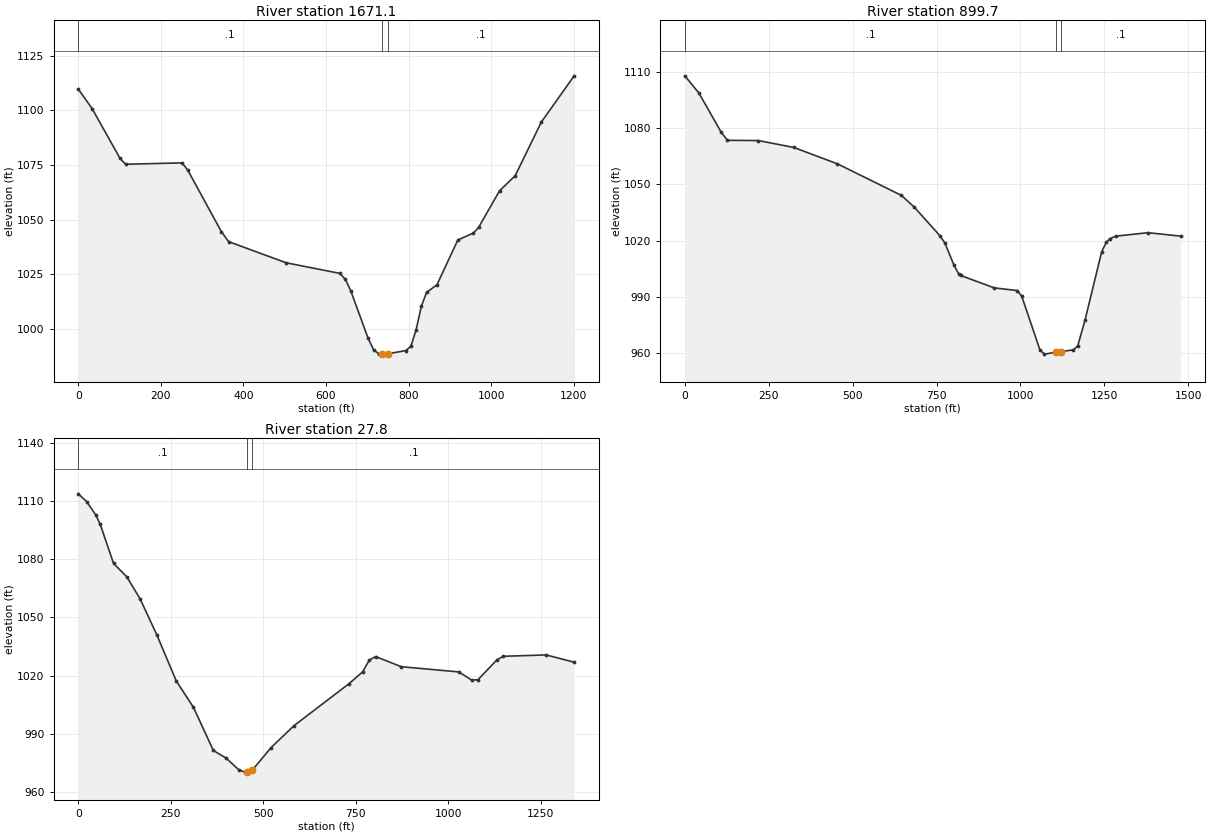
Type RM Length L Ch R = 1 ,1671.1,762.209,771.367,785.08
XS GIS Cut Line= 3
     1737659.344      283951.618     1737293.034      284598.307
     1737135.732      285028.996
#Sta/Elev= 30
       0 1109.62    33.3 1100.78   101.1 1077.98   114.7 1075.33   251.2 1075.97
   264.8 1072.75   346.5 1044.57   364.0 1039.99   503.4 1030.34   633.2 1025.51
   646.9 1022.82   660.5 1017.29   701.5  996.09   715.1  990.69   728.7  988.62
   735.7  988.65   750.7  988.81   793.0  990.23   805.6  992.17   818.3  999.73
   831.0 1010.43   843.6 1016.78   868.8 1020.29   919.4 1040.74   957.3 1043.93
   970.0 1046.57  1020.5 1063.24  1058.4 1070.11  1121.6 1094.58  1201.2 1115.72
#Mann= 3 , 0 , 0
       0     0.1       0   735.7   0.045       0   750.7     0.1       0
Bank Sta=   735.7,   750.7
Exp/Cntr=0.3,0.1

Type RM Length L Ch R = 1 ,899.7,866.649,871.965,874.952
XS GIS Cut Line= 6
     1737631.482      283956.856     1737442.132      284119.156
     1736992.397      284293.869     1736981.990      284299.498
     1736687.145      284457.358     1736354.840      284678.365
#Sta/Elev= 30
       0 1107.83    42.1 1098.63   108.8 1077.65   127.1 1073.45   219.5 1073.31
   324.7 1069.64   454.3 1060.94   645.4 1044.07   683.6 1037.86   761.6 1022.25
   775.1 1018.57   802.0 1006.89   815.5 1002.36   821.8 1001.40   922.4  994.74
   990.6  993.36  1004.0  990.25  1057.9  961.75  1071.4  959.45  1106.8  960.47
  1121.8  960.83  1157.8  961.74  1170.8  963.93  1192.1  977.39  1242.1 1014.10
  1256.3 1019.21  1267.0 1021.09  1284.9 1022.37  1380.5 1024.20  1477.2 1022.36
#Mann= 3 , 0 , 0
       0     0.1       0  1106.8   0.045       0  1121.8     0.1       0
Bank Sta=  1106.8,  1121.8
Exp/Cntr=0.3,0.1

Type RM Length L Ch R = 1 ,27.8,31.429,27.754,24.064
XS GIS Cut Line= 4
     1737440.133      283866.923     1737079.212      283812.590
     1736693.751      283932.061     1736277.991      284325.656
#Sta/Elev= 30
       0 1113.61    23.0 1109.50    47.1 1102.74    59.1 1097.99    95.1 1077.87
   131.1 1070.87   167.1 1059.53   212.7 1040.85   264.8 1017.30   311.2 1003.78
   365.0  981.58   399.5  977.62   433.6  971.68   449.9  970.42   455.6  970.48
   470.6  971.49   520.6  982.96   582.8  994.27   731.9 1015.94   768.5 1021.98
   786.7 1028.08   804.0 1029.87   873.1 1024.66  1028.5 1021.98  1063.1 1017.83
  1080.3 1017.93  1132.1 1028.27  1149.4 1030.02  1264.9 1030.72  1340.5 1026.97
#Mann= 3 , 0 , 0
       0     0.1       0   455.6   0.045       0   470.6     0.1       0
Bank Sta=   455.6,   470.6
Exp/Cntr=0.3,0.1